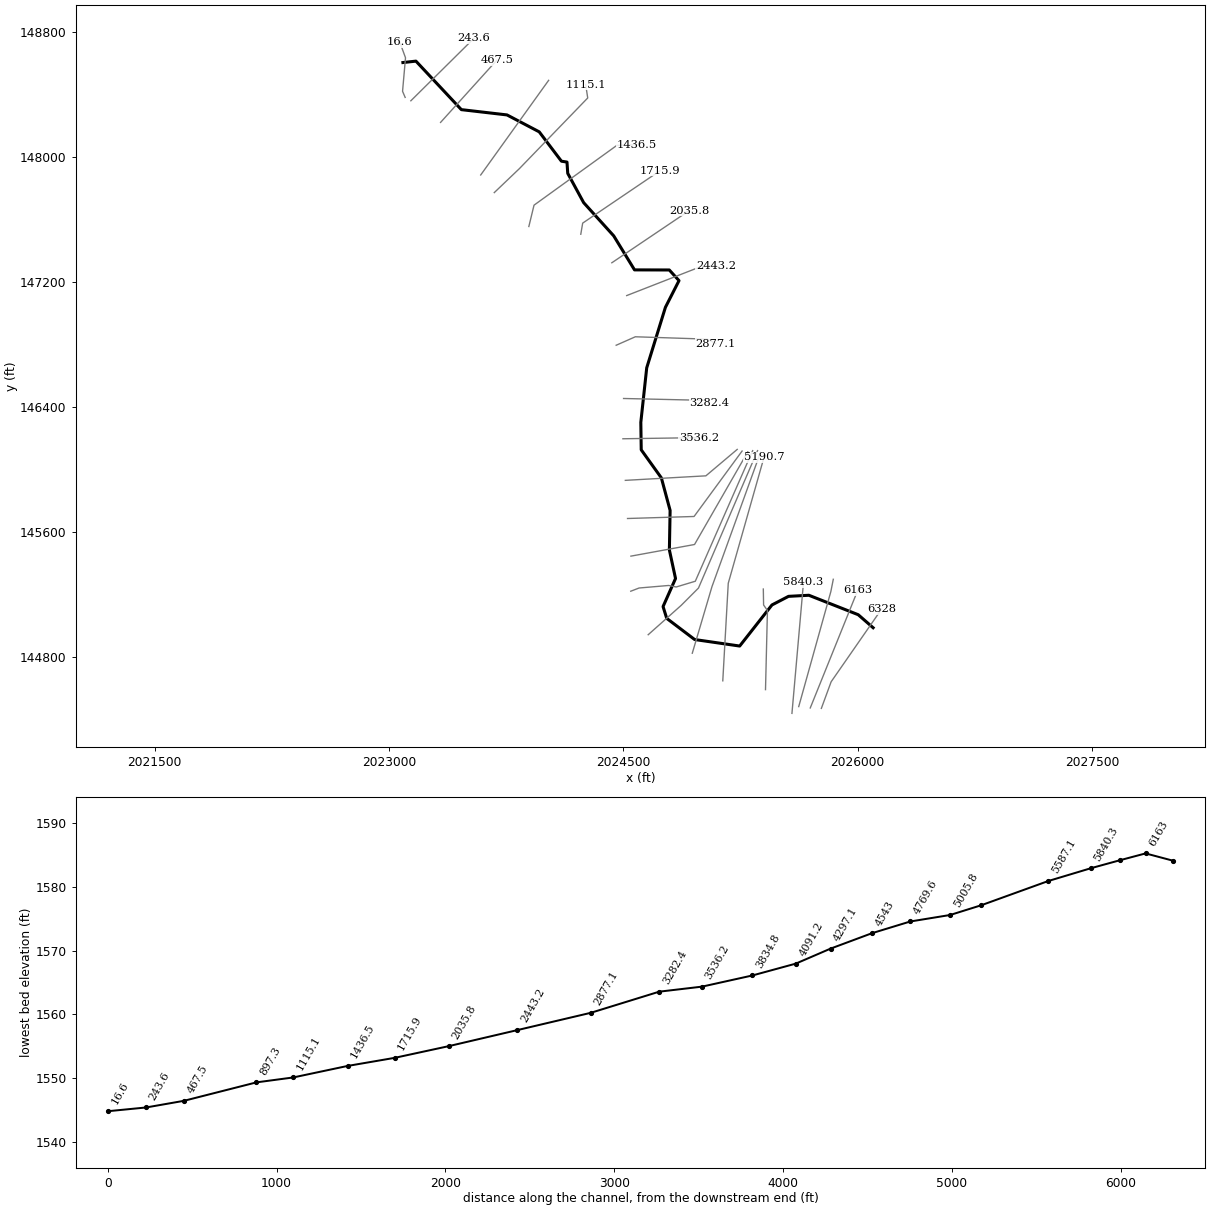
--- RICHCK2.prj (project) ---

Proj Title=RICHCK2
Current Plan=p01
Default Exp/Contr=0,0
English Units
Geom File=g01
Flow File=f01
Plan File=p01
BEGIN DESCRIPTION:
END DESCRIPTION:
DSS Export Rating Curves= 0
DSS Export Rating Curve Sorted= 0
DSS Export Volume Flow Curves= 0
DXF OffsetX= 0
DXF OffsetY= 0
DXF ScaleX= 0
DXF ScaleY= 0

--- RICHCK2.p01 (plan) ---

Plan Title=Floodplain
Program Version=4.00
Geom File=g01
Flow File=f01
K Sum by GR=0
Std Step Tol=0.01
Critical Tol=0.01
Num of Std Step Trials=20
Max Error Tol=0.3
Flow Tol Ratio=0.001
Split Flow NTrial=30
Split Flow Tol=0.02
Split Flow Ratio=0.02
Log Output Level=0
Friction Slope Method=1
Unsteady Friction Slope Method=2
Unsteady Bridges Friction Slope Method=1
Global Log Level=0
CheckData=False
Run HTab=0
Run UNet=0
Run PostProcess=0
UNET Theta=0
UNET Theta Warmup=0
UNET ZTol=0
UNET ZSATol=0
UNET MxIter=0
UNET MaxInSteps=0
UNET DtIC=0
UNET DtMin=0
UNET MaxCRTS=0
UNET WFStab=0
UNET SFStab=0
UNET WFX=0
UNET SFX=0
UNET DSS MLevel=0
UNET DZMax Abort=0
UNET Convert EG Bridges=0
UNET Use Existing IB Tables=0
UNET Froude Limit=0
UNET Froude Power=0
Write IC File=0
Echo Input=False
Echo Output=False
Write Detailed=0

--- RICHCK2.f01 (steady flow) ---

Flow Title=NFF Regression Equation
Program Version=4.10
Number of Profiles= 1
Profile Names=P100yr
River Rch & RM=RICHCK2,Main            ,6328
    4070
Boundary for River Rch & Prof#=RICHCK2,Main            , 1
Up Type= 0
Dn Type= 3
Dn Slope=0.00255
DSS Import GetInterval= 0
DSS Import GetPeak= 0
DSS Import FillOption= 0

--- RICHCK2.g01 (geometry) ---

Geom Title=USGS 10m DEM
Program Version=4.10

River Reach=RICHCK2         ,Main
Reach XY= 30
     2026099.382      144985.618     2026003.896      145068.951
     2025688.086       145193.46     2025557.878      145186.515
     2025451.813      145131.451     2025245.216      144868.431
     2024957.021      144910.097     2024778.202      145045.514
     2024754.764      145121.035     2024834.625      145300.722
     2024795.235      145483.356     2024799.903      145736.486
     2024743.914       145944.82     2024615.007      146124.507
     2024612.403      146300.288     2024650.164      146649.247
     2024769.857      147036.515     2024856.836      147207.348
     2024794.695      147275.549     2024572.114      147276.098
     2024438.867       147493.98     2024246.518      147706.538
     2024144.596      147894.154     2024139.822      147966.203
     2024104.232      147971.845     2023962.143      148159.663
     2023755.893      148267.997     2023463.705      148301.851
     2023172.982      148612.296     2023089.648      148603.269

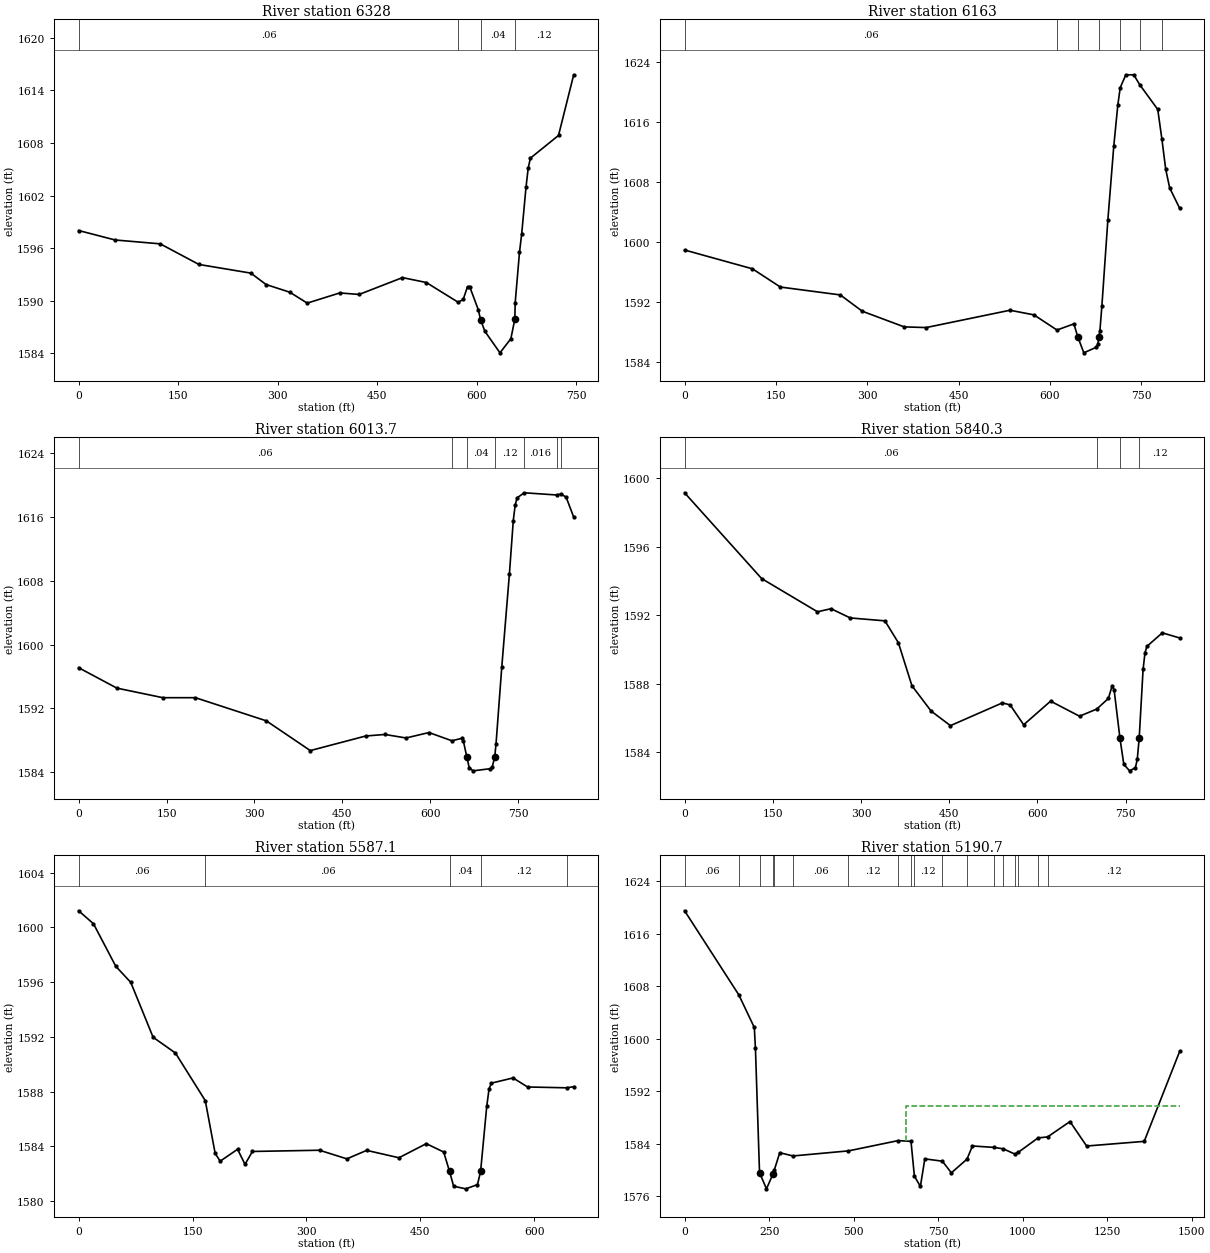
Type RM Length L Ch R = 1 ,6328    ,156.2,165,173.9
XS GIS Cut Line= 3
     2025768.018       144469.42     2025830.518      144639.559
     2026152.595      145103.527
#Sta/Elev= 30
       0 1598.01      55 1596.93     123 1596.49   181.3 1594.14   259.6 1593.15
   282.5 1591.85   318.4 1590.97   344.5 1589.73   393.5 1590.89   422.8 1590.72
   488.1 1592.64     524 1592.08  572.031589.827   579.6 1590.15   586.1 1591.61
   589.4  1591.6   602.4 1588.96   605.7 1587.85   612.2 1586.52     635 1584.06
   651.4 1585.67  657.43 1587.92   657.9 1589.75   664.4 1595.52   667.7 1597.61
   674.2 1602.92   677.5  1605.1   680.8 1606.26   723.2 1608.85   746.1 1615.77
#Mann= 4 ,-1 , 0
       0     .06       0  572.03     .12       0   605.7     .04       0
  657.43     .12       0
Bank Sta=605.7,657.43
XS Rating Curve= 0 ,0
Exp/Cntr=0.3,0.1

Type RM Length L Ch R = 1 ,6163    ,144.8,149.3,153.8
XS GIS Cut Line= 2
     2025696.941      144472.165      2026001.29       145226.31
#Sta/Elev= 30
       0 1598.93   111.5 1596.42   157.4 1593.99   255.8 1592.94   291.8 1590.77
   360.7 1588.68   396.8 1588.59   534.5  1590.9   573.9 1590.28  611.671588.261
   639.4 1589.08     646 1587.32   655.8 1585.22   675.5 1585.94   678.8 1586.36
  680.34 1587.36   682.1 1588.07   685.4 1591.43   695.2 1602.88     705  1612.8
   711.6 1618.25  715.531620.567   724.7 1622.28   737.8 1622.29  747.391620.991
   777.2 1617.67  784.061613.684   790.3 1609.68   796.8 1607.21   813.2 1604.49
#Mann= 7 ,-1 , 0
       0     .06       0  611.67     .12       0     646     .04       0
  680.34     .12       0  715.53     .08       0  747.39     .06       0
  784.06     .12       0
Bank Sta=646,680.34
XS Rating Curve= 0 ,0
Exp/Cntr=0.3,0.1

Type RM Length L Ch R = 1 ,6013.7  ,166,173.5,180.8
XS GIS Cut Line= 3
     2025623.157      144480.845     2025828.739      145217.138
     2025844.407      145295.809
#Sta/Elev= 30
       0  1597.1    65.3 1594.54   143.7 1593.34   199.3 1593.34   320.2 1590.44
   395.3 1586.71     490 1588.54   522.7 1588.73   558.6 1588.29   597.8 1588.97
  636.831587.939   653.4 1588.24   656.6 1587.86  662.48 1585.87   666.4 1584.57
     673 1584.17   702.4 1584.44   705.6 1584.62  709.91  1585.9   712.2 1587.57
     722  1597.2     735 1608.84   741.6 1615.53   744.8 1617.46   748.1  1618.4
  760.611619.029  815.361618.753   822.91618.874   831.8 1618.48   844.7 1615.98
#Mann= 7 ,-1 , 0
       0     .06       0  636.83     .12       0  662.48     .04       0
  709.91     .12       0  760.61    .016       0  815.36     .08       0
   822.9    .016       0
Bank Sta=662.48,709.91
XS Rating Curve= 0 ,0
Exp/Cntr=0.3,0.1

Type RM Length L Ch R = 1 ,5840.3  ,250.7,253.2,276.5
XS GIS Cut Line= 2
     2025579.754      144437.443     2025653.699      145276.087
#Sta/Elev= 30
       0 1599.15     131 1594.14     226  1592.2     249 1592.38   281.7 1591.84
   340.7 1591.67   363.6 1590.39   386.6 1587.88   419.3  1586.4   452.1 1585.55
   540.5 1586.88   553.6 1586.76   576.6  1585.6   622.4 1586.98   671.6  1586.1
  700.951586.519   720.7 1587.14   727.2 1587.89   730.5 1587.62   740.4  1584.8
   746.9 1583.29   756.7 1582.91   766.6 1583.09   769.8 1583.58   773.1 1584.83
   779.7 1588.84   782.9  1589.8   786.2 1590.18   812.4 1590.97   841.9 1590.67
#Mann= 4 ,-1 , 0
       0     .06       0  700.95     .12       0   740.4     .04       0
   773.1     .12       0
Bank Sta=740.4,773.1
XS Rating Curve= 0 ,0
Exp/Cntr=0.3,0.1

Type RM Length L Ch R = 1 ,5587.1  ,398.2,396.4,373.5
XS GIS Cut Line= 4
     2025410.483      144589.352     2025422.893      145096.029
     2025398.259      145131.035      2025396.49      145233.309
#Sta/Elev= 30
       0 1601.21    19.6 1600.26      49 1597.15    68.7 1595.98    98.1 1591.97
   127.5 1590.82   166.8 1587.34   179.8 1583.49   186.4 1582.92   209.3 1583.79
   219.1 1582.69   228.9 1583.63   317.2 1583.72   353.2 1583.09   379.3 1583.71
   421.8 1583.17   457.8  1584.2   480.7 1583.59  488.43 1582.17   493.8 1581.09
   509.9  1580.9   525.2 1581.21  529.31 1582.17   537.4 1586.93   540.5 1588.22
   543.5 1588.62     572    1589   591.2 1588.34  642.711588.279   651.9 1588.36
#Mann= 5 ,-1 , 0
       0     .06       0   166.8     .06       0  488.43     .04       0
  529.31     .12       0  642.71    .016       0
Bank Sta=488.43,529.31
XS Rating Curve= 0 ,0
Exp/Cntr=0.3,0.1

Type RM Length L Ch R = 1 ,5190.7  ,194.2,184.9,175.6
XS GIS Cut Line= 3
     2025137.046      144645.776     2025172.069      145270.231
     2025401.235      146077.522
#Sta/Elev= 30
       0 1619.52   160.4  1606.7   206.3 1601.72   209.6 1598.58  221.75 1579.57
   242.3 1577.11   261.9 1579.42  265.771580.041   281.6 1582.62  320.761582.126
  484.781582.899  631.581584.464   669.81584.355  679.841579.049   697.6 1577.48
   710.7 1581.68  762.541581.329   789.3 1579.55  835.491581.644   851.6 1583.65
  915.461583.428  942.96 1583.21  976.871582.414  986.741582.666 1045.741584.879
 1073.841585.028  1140.1 1587.37  1189.3 1583.64  1359.7 1584.35  1464.6 1598.07
#Mann= 18 ,-1 , 0
       0     .06       0   160.4      .1       0  221.75     .04       0
   261.9      .1       0  265.77     .12       0  320.76     .06       0
  484.78     .12       0  631.58    .016       0   669.8     .08       0
  679.84     .12       0  762.54     .06       0  835.49     .12       0
  915.46    .016       0  942.96     .12       0  976.87     .06       0
  986.74    .016       0 1045.74     .06       0 1073.84     .12       0
#XS Ineff= 2 , 0
                          656.29          1589.7
Permanent Ineff=
       F       F
Bank Sta=221.75,261.9
XS Rating Curve= 0 ,0
Exp/Cntr=0.3,0.1

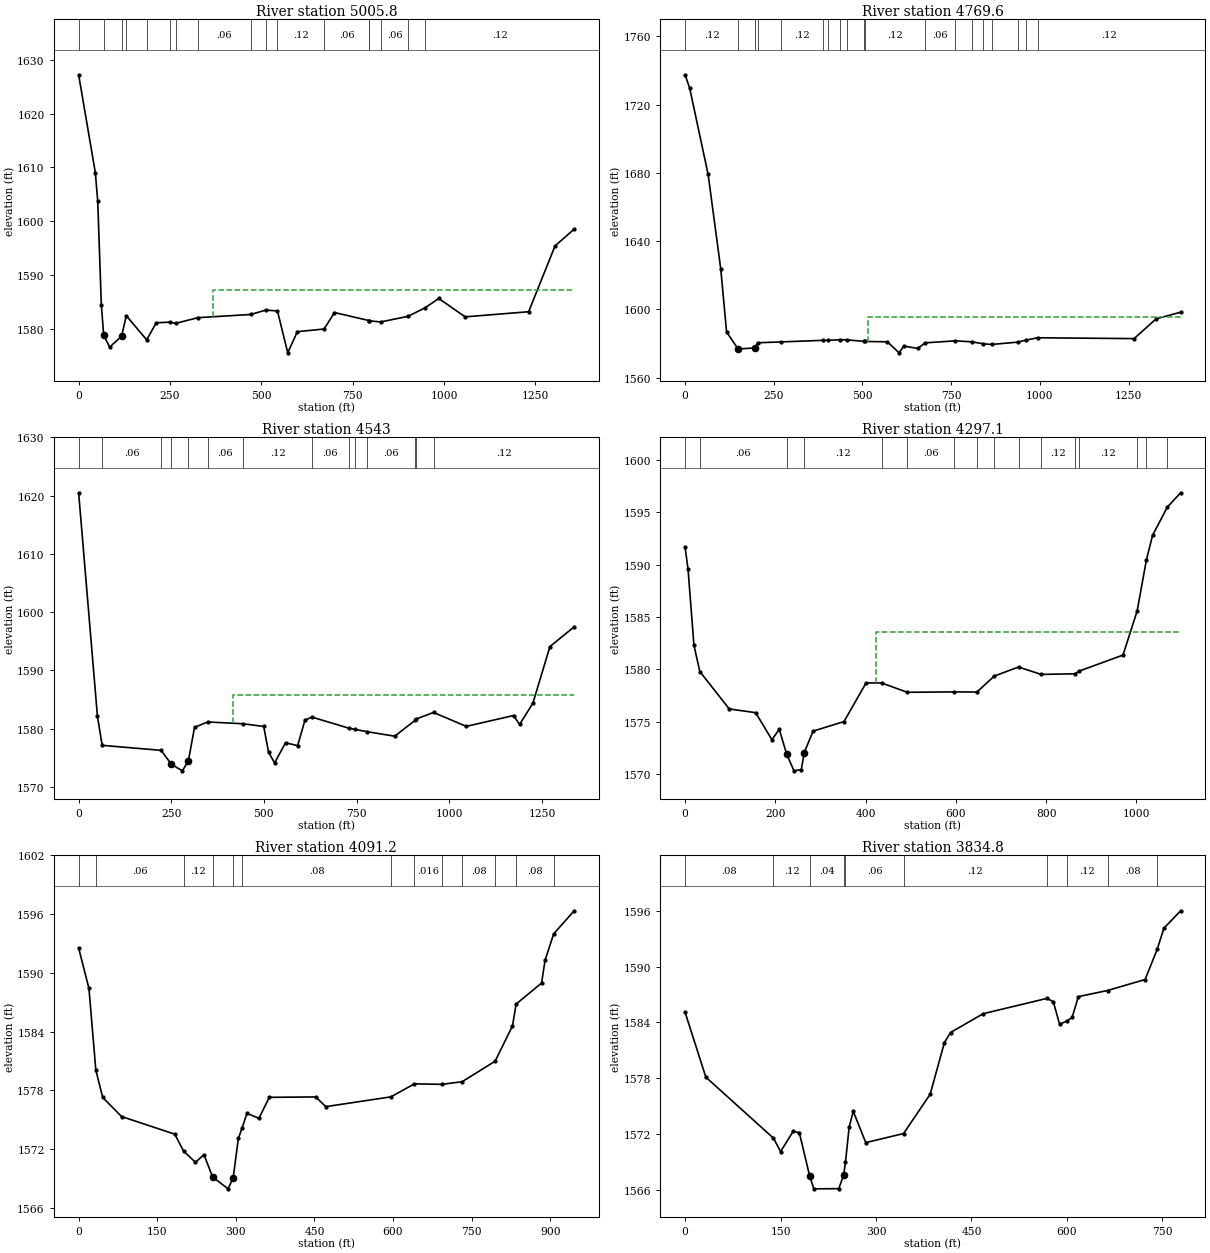
Type RM Length L Ch R = 1 ,5005.8  ,258.6,236.2,213.8
XS GIS Cut Line= 3
     2024941.845      144822.464     2025067.842      145248.645
     2025377.798      146106.168
#Sta/Elev= 30
       0 1627.19    45.8    1609    52.3 1603.67    62.1 1584.54    68.6 1578.82
      85 1576.65   117.6 1578.66  130.471582.468  186.23 1577.99   212.4 1581.16
  249.741581.277  265.691581.054   326.61582.109  470.66  1582.7  512.741583.518
  544.151583.353   572.3 1575.58   598.6 1579.51  671.861580.001   700.2 1583.06
   794.71581.572  795.441581.527  826.851581.315  901.541582.358   947.91583.932
   985.6 1585.67  1057.8 1582.26  1231.6 1583.21  1303.8 1595.42  1356.2 1598.54
#Mann= 17 ,-1 , 0
       0     .12       0    68.6     .04       0   117.6     .04       0
  130.47     .12       0  186.23     .04       0  249.74     .06       0
  265.69     .12       0   326.6     .06       0  470.66     .08       0
  512.74    .016       0  544.15     .12       0  671.86     .06       0
   794.7     .12       0  795.44    .016       0  826.85     .06       0
  901.54    .016       0   947.9     .12       0
#XS Ineff= 2 , 0
                          368.32         1587.25
Permanent Ineff=
       F       F
Bank Sta=68.6,117.6
XS Rating Curve= 0 ,0
Exp/Cntr=0.3,0.1

Type RM Length L Ch R = 1 ,4769.6  ,259,226.6,202.1
XS GIS Cut Line= 4
     2024659.615      144940.915     2024870.625      145128.655
     2024981.401      145239.543     2025359.569      146119.189
#Sta/Elev= 30
       0 1737.46      13 1729.56    64.9 1679.09   100.6 1623.57   116.9  1586.8
   149.3 1576.85     198 1577.42  204.091580.458  270.891580.963  387.831581.889
  402.811581.861  437.411582.266  455.921582.175  504.83 1581.26  508.211581.217
   570.3 1581.02   603.1 1574.56   616.2 1578.51   655.6 1577.15  676.831580.412
   761.51581.588  808.421581.016  840.581579.845  863.721579.471  937.041580.824
  959.511581.938  993.541583.394  1265.5 1582.89  1327.8 1594.52  1396.7 1598.34
#Mann= 19 ,-1 , 0
       0     .12       0   149.3     .04       0     198     .12       0
  204.09     .06       0  270.89     .12       0  387.83     .06       0
  402.81     .12       0  437.41     .06       0  455.92     .12       0
  504.83     .06       0  508.21     .12       0  676.83     .06       0
   761.5     .12       0  808.42    .016       0  840.58     .12       0
  863.72     .06       0  937.04     .12       0  959.51    .016       0
  993.54     .12       0
#XS Ineff= 2 , 0
                          514.85         1595.82
Permanent Ineff=
       F       F
Bank Sta=149.3,198
XS Rating Curve= 0 ,0
Exp/Cntr=0.3,0.1

Type RM Length L Ch R = 1 ,4543    ,235.3,245.8,247.5
XS GIS Cut Line= 6
     2024548.013      145219.302     2024601.182      145239.918
     2024791.069      145256.194     2024838.812      145246.429
     2024961.131      145283.252     2025328.319      146119.189
#Sta/Elev= 30
       0 1620.49    50.7 1582.13    63.5 1577.11  222.471576.251   250.5 1573.84
   280.1 1572.73   296.3  1574.5   312.7  1580.2  348.231581.123  443.64 1580.82
   499.4 1580.35   512.4 1575.95   528.8 1574.08   558.2 1577.55     591 1577.06
   610.6 1581.42   629.31581.966  729.111580.056  746.851579.837  779.11 1579.45
   852.8 1578.68  908.171581.418  909.92 1581.61  957.531582.759  1045.9 1580.37
  1173.5 1582.23  1189.8 1580.69  1225.8 1584.36  1271.7 1594.08  1337.1 1597.46
#Mann= 14 ,-1 , 0
       0     .12       0    63.5     .06       0  222.47     .12       0
   250.5     .04       0   296.3     .12       0  348.23     .06       0
  443.64     .12       0   629.3     .06       0  729.11     .12       0
  746.85    .016       0  779.11     .06       0  908.17     .12       0
  909.92    .016       0  957.53     .12       0
#XS Ineff= 2 , 0
                          415.84         1585.79
Permanent Ineff=
       F       F
Bank Sta=250.5,296.3
XS Rating Curve= 0 ,0
Exp/Cntr=0.3,0.1

Type RM Length L Ch R = 1 ,4297.1  ,211.4,206,199.3
XS GIS Cut Line= 3
     2024549.098      145443.911     2024956.259      145518.392
     2025297.069      146111.377
#Sta/Elev= 30
       0 1591.65     6.5 1589.56    19.6  1582.3    32.6 1579.79    97.8 1576.22
   156.4 1575.86   192.3 1573.28   208.6 1574.27   224.9 1571.92   241.2 1570.31
   257.5 1570.43     264 1572.06   283.6  1574.1     352 1575.01   400.9  1578.7
  435.311578.699  492.231577.807  595.441577.845   646.51577.831  685.041579.357
  738.741580.218  788.891579.513     8641579.573  872.571579.823   970.2 1581.36
 1001.49 1585.56 1021.881590.402  1035.7 1592.79 1068.651595.497  1097.9 1596.85
#Mann= 16 ,-1 , 0
       0     .12       0    32.6     .06       0   224.9     .04       0
     264     .12       0  435.31    .016       0  492.23     .06       0
  595.44     .12       0   646.5     .08       0  685.04     .12       0
  738.74    .016       0  788.89     .12       0     864     .08       0
  872.57     .12       0 1001.49     .06       0 1021.88     .12       0
 1068.65     .06       0
#XS Ineff= 2 , 0
                          422.63         1583.52
Permanent Ineff=
       F       F
Bank Sta=224.9,264
XS Rating Curve= 0 ,0
Exp/Cntr=0.3,0.1

Type RM Length L Ch R = 1 ,4091.2  ,258.2,256.4,257.4
XS GIS Cut Line= 3
     2024527.397      145684.797     2024953.227       145697.73
      2025260.61      146116.585
#Sta/Elev= 30
       0 1592.54    19.7 1588.41    32.8 1580.09    45.9 1577.29    81.9 1575.34
   183.5 1573.54  200.14 1571.82   222.8 1570.67   239.2 1571.44   255.6 1569.18
   285.1 1567.96   294.9 1569.08   304.8  1573.1  311.79 1574.15   321.2 1575.66
   344.1 1575.16   363.8  1577.3   452.2 1577.34   471.8 1576.35  595.821577.347
  640.811578.677  693.461578.625  731.941578.896  794.761580.988   827.9 1584.59
  834.861586.822   883.5 1588.97     890 1591.29  906.59 1593.99   945.6 1596.34
#Mann= 13 ,-1 , 0
       0     .12       0    32.8     .06       0  200.14     .12       0
   255.6     .04       0   294.9     .12       0  311.79     .08       0
  595.82     .12       0  640.81    .016       0  693.46     .12       0
  731.94     .08       0  794.76     .12       0  834.86     .08       0
  906.59     .06       0
Bank Sta=255.6,294.9
XS Rating Curve= 0 ,0
Exp/Cntr=0.3,0.1

Type RM Length L Ch R = 1 ,3834.8  ,297.2,298.5,297
XS GIS Cut Line= 4
     2024513.291      145928.937     2024900.996      145950.808
     2025028.831      145957.874      2025229.36      146127.002
#Sta/Elev= 30
       0 1585.09    32.6 1578.12  138.791571.563   150.1 1570.12   169.7 1572.28
   179.5 1572.15   195.8 1567.47   202.3 1566.11   241.5 1566.13  249.18  1567.6
  252.041568.983   257.8 1572.76   264.3 1574.44   283.9 1571.08  343.281572.054
   385.1 1576.28   407.5 1581.84   417.1 1582.92   468.3 1584.94  568.561586.589
   578.6 1586.24   588.5  1583.8  599.911584.164   608.2 1584.54     618 1586.78
   663.81587.437   722.9 1588.62  741.921591.883   752.4 1594.13   778.7 1596.01
#Mann= 10 ,-1 , 0
       0     .08       0  138.79     .12       0   195.8     .04       0
  249.18     .12       0  252.04     .06       0  343.28     .12       0
  568.56    .016       0  599.91     .12       0   663.8     .08       0
  741.92     .06       0
Bank Sta=195.8,249.18
XS Rating Curve= 0 ,0
Exp/Cntr=0.3,0.1

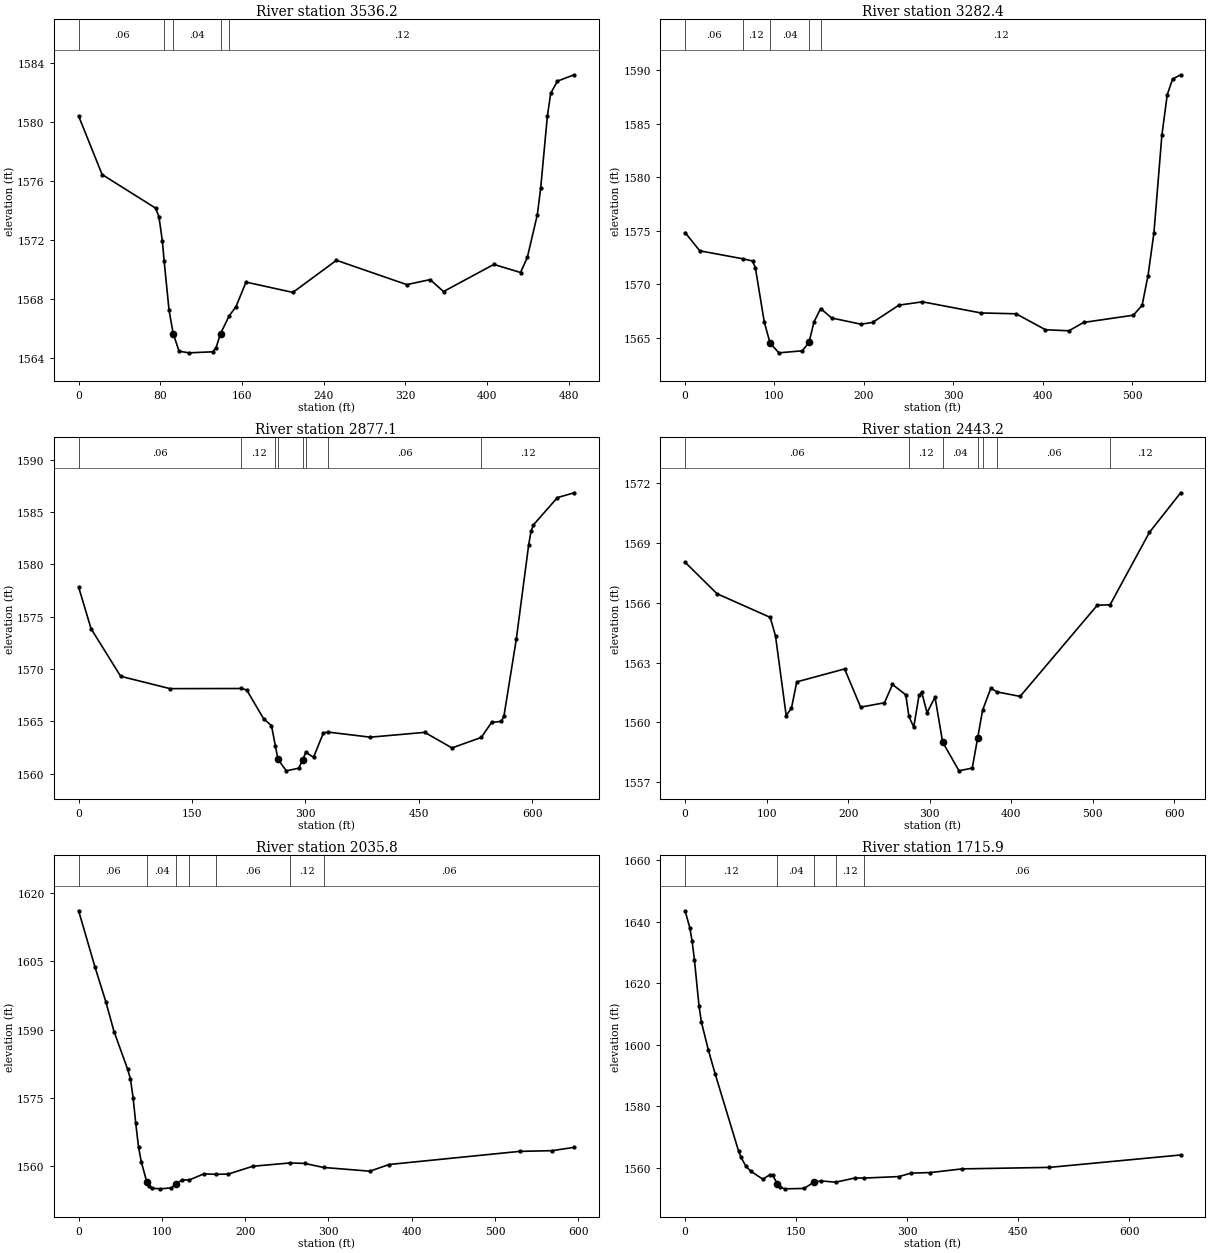
Type RM Length L Ch R = 1 ,3536.2  ,255.4,253.8,252.3
XS GIS Cut Line= 2
     2024497.708      146195.148     2024983.126      146202.375
#Sta/Elev= 30
       0 1580.43      23 1576.46    75.4 1574.18    78.7 1573.59      82 1571.97
   83.791570.576    88.6 1567.24   92.71 1565.65    98.4 1564.47   108.2 1564.36
   131.2 1564.43   134.5 1564.68     139 1565.66   147.41566.858   154.2  1567.5
     164 1569.16   209.9 1568.46   252.6 1570.64   321.5 1568.99   344.4 1569.33
   357.5 1568.52   406.8 1570.36     433 1569.81   439.6 1570.84   449.4 1573.73
   452.7 1575.55   459.2  1580.4   462.5 1581.97   469.1  1582.8   485.5 1583.23
#Mann= 5 ,-1 , 0
       0     .06       0   83.79     .12       0   92.71     .04       0
     139     .04       0   147.4     .12       0
Bank Sta=92.71,139
XS Rating Curve= 0 ,0
Exp/Cntr=0.3,0.1

Type RM Length L Ch R = 1 ,3282.4  ,405.6,405.3,405
XS GIS Cut Line= 3
     2024502.048      146452.961      2025026.27      146440.938
     2025051.486      146424.814
#Sta/Elev= 30
       0 1574.82    16.4 1573.11   64.241572.368    75.4 1572.16    78.6 1571.53
    88.5 1566.48      95 1564.49   104.9 1563.57   131.1 1563.76   138.6 1564.55
   144.2 1566.46  151.631567.711   163.9 1566.83   196.6 1566.25   209.7 1566.41
   239.2 1568.03   265.5 1568.34     331  1567.3   370.3 1567.22   403.1 1565.73
   429.3 1565.63   445.7 1566.41   501.4 1567.09   511.2 1568.01   517.8 1570.79
   524.4 1574.77   533.3  1583.9   539.3  1587.7   545.3 1589.17   554.3 1589.57
#Mann= 5 ,-1 , 0
       0     .06       0   64.24     .12       0      95     .04       0
   138.6     .04       0  151.63     .12       0
Bank Sta=95,138.6
XS Rating Curve= 0 ,0
Exp/Cntr=0.3,0.1

Type RM Length L Ch R = 1 ,2877.1  ,415.1,433.9,449.5
XS GIS Cut Line= 4
     2024454.697      146793.738      2024577.31      146847.991
     2025038.465        146832.8     2025091.633      146804.588
#Sta/Elev= 30
       0 1577.83    16.4 1573.86    55.6  1569.3     121 1568.12  215.471568.134
   222.4 1567.99   244.7 1565.25   255.2 1564.58  260.43 1562.61  263.75 1561.36
   274.8 1560.26   291.2 1560.51  296.57 1561.33  300.631562.036   310.8 1561.55
   323.9 1563.89  330.191563.963     386 1563.48     458 1563.94     494 1562.45
  532.771563.455   546.4 1564.89   559.5 1564.99   562.8 1565.51   579.1 1572.84
   595.5 1581.87   598.6 1583.17   601.8 1583.78   633.5 1586.39   655.7 1586.85
#Mann= 8 ,-1 , 0
       0     .06       0  215.47     .12       0  260.43     .04       0
  263.75     .04       0  296.57     .04       0  300.63     .12       0
  330.19     .06       0  532.77     .12       0
Bank Sta=263.75,296.57
XS Rating Curve= 0 ,0
Exp/Cntr=0.3,0.1

Type RM Length L Ch R = 1 ,2443.2  ,398.3,407.4,414
XS GIS Cut Line= 3
     2024521.972      147111.663     2025008.083       147301.55
     2025094.062      147301.919
#Sta/Elev= 30
       0 1568.04    39.1 1566.46   104.4 1565.27   110.9 1564.34     124 1560.34
   130.5 1560.71     137 1562.03   195.7 1562.68   215.3 1560.76   244.6 1560.98
   254.4  1561.9   270.7 1561.38  274.571560.291   280.5 1559.76     287 1561.36
   290.3  1561.5   296.8 1560.48   306.6 1561.26   315.9 1559.01     336 1557.56
   352.3  1557.7   358.8 1559.19  364.96 1560.61   375.1 1561.71  382.481561.527
     411  1561.3   505.6 1565.88  521.381565.905   569.6 1569.54   607.9 1571.53
#Mann= 7 ,-1 , 0
       0     .06       0  274.57     .12       0   315.9     .04       0
   358.8     .04       0  364.96     .12       0  382.48     .06       0
  521.38     .12       0
Bank Sta=315.9,358.8
XS Rating Curve= 0 ,0
Exp/Cntr=0.3,0.1

Type RM Length L Ch R = 1 ,2035.8  ,319.5,319.9,319.7
XS GIS Cut Line= 2
      2024426.84      147321.606     2024920.192      147654.198
#Sta/Elev= 30
       0 1616.05    19.6 1603.72    32.7 1596.07    42.5 1589.55    58.8  1581.3
    62.1 1579.24    65.4 1575.07    68.6 1569.38    71.9 1564.23    75.2 1561.01
    81.7 1556.62      85 1555.57    88.3 1555.17    98.1 1555.04   111.2 1555.25
   117.4 1556.14   124.2 1556.99  132.821556.983   150.4 1558.33  164.351558.225
   179.8 1558.28   209.2    1560  253.941560.721   271.3 1560.62  294.091559.731
   349.8 1558.91   372.7 1560.38   529.6 1563.26   568.8 1563.42     595 1564.15
#Mann= 7 ,-1 , 0
       0     .06       0    81.7     .04       0   117.4     .04       0
  132.82     .12       0  164.35     .06       0  253.94     .12       0
  294.09     .06       0
Bank Sta=81.7,117.4
XS Rating Curve= 0 ,0
Exp/Cntr=0.3,0.1

Type RM Length L Ch R = 1 ,1715.9  ,278.1,279.4,280.6
XS GIS Cut Line= 3
      2024228.12      147504.299     2024240.273      147575.479
     2024734.645      147910.274
#Sta/Elev= 30
       0 1643.54     6.3 1638.06     9.4 1633.82    12.6 1627.59    18.8 1612.65
      22 1607.41    31.4  1598.3    40.8  1590.4    72.2  1565.5    75.5 1563.42
      82 1560.64    88.6 1558.94     105 1556.35   114.9 1557.86   118.1 1557.61
   124.7 1554.89     128 1553.82   134.5 1553.21   160.8 1553.34   173.9 1555.38
   183.8 1555.78  203.35 1555.37   229.7 1556.75  241.61 1556.71   288.7 1557.19
   305.1 1558.31   331.4  1558.5     374 1559.69   492.1 1560.18   669.3 1564.21
#Mann= 5 ,-1 , 0
       0     .12       0   124.7     .04       0   173.9     .04       0
  203.35     .12       0  241.61     .06       0
Bank Sta=124.7,173.9
XS Rating Curve= 0 ,0
Exp/Cntr=0.3,0.1

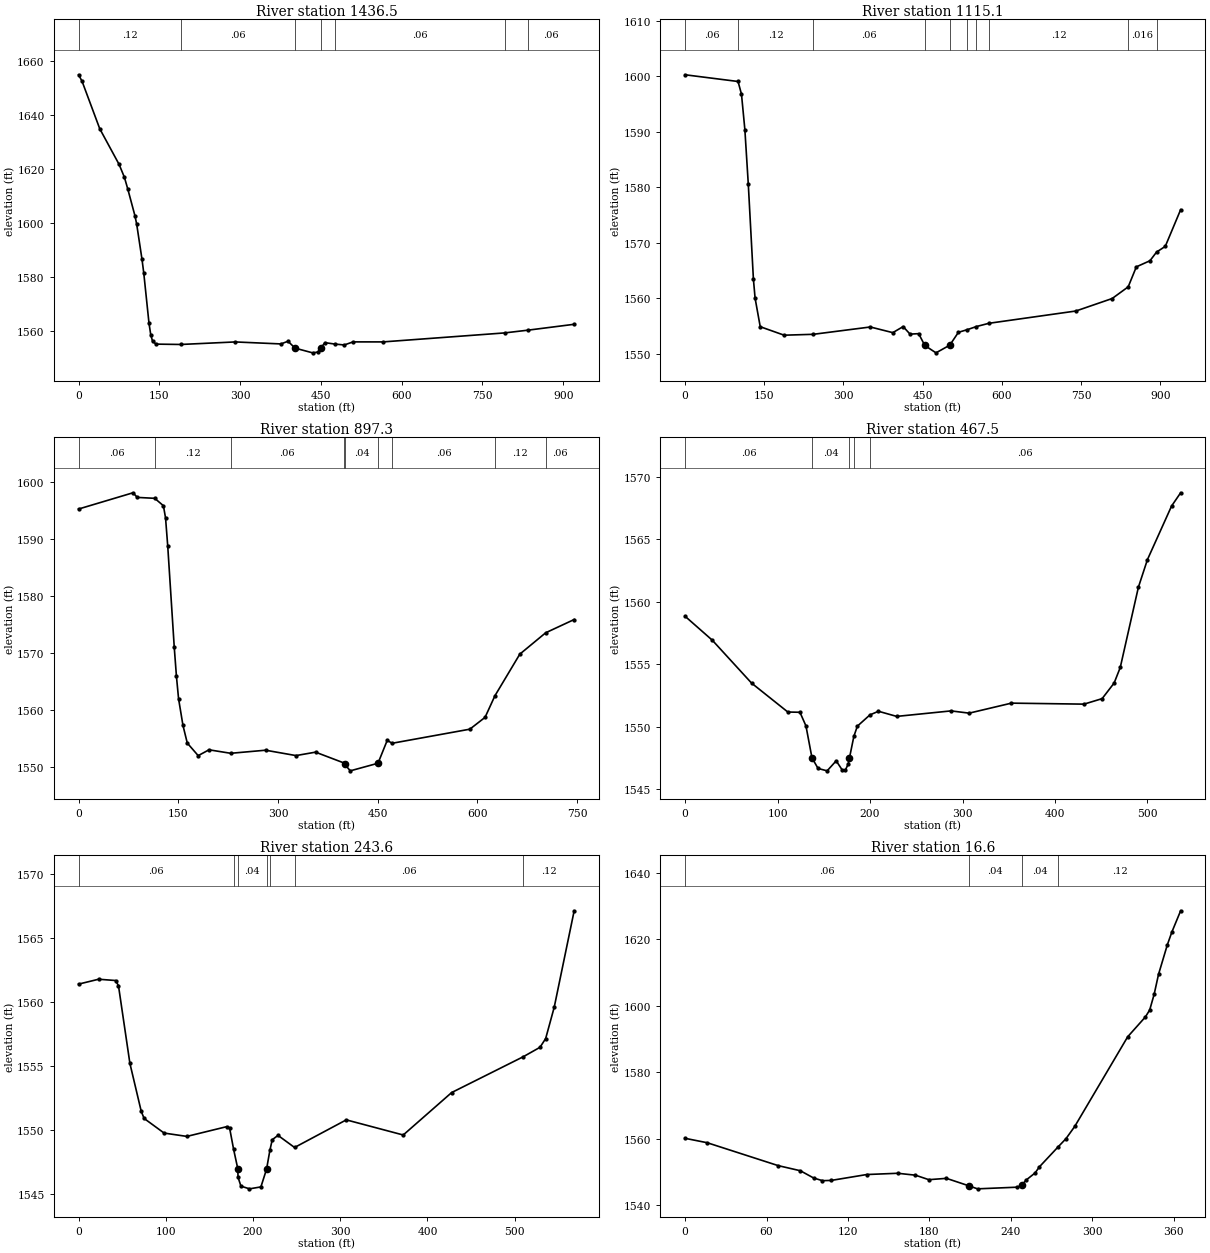
Type RM Length L Ch R = 1 ,1436.5  ,297.4,321.4,324.6
XS GIS Cut Line= 4
     2023895.726      147553.762     2023928.825      147690.342
     2024458.691      148072.848     2024584.906       148078.46
#Sta/Elev= 30
       0 1654.98     6.5  1652.5    39.2 1634.99    75.2 1621.75      85    1617
    91.5  1612.5   104.6 1602.73   107.8 1599.66   117.7 1586.59   120.9 1581.65
   130.7  1562.9     134 1558.59   137.3 1556.24   143.8 1555.17   189.6 1555.04
   290.8 1555.98   375.8 1555.24   388.9 1556.24   401.9 1553.69   434.6 1551.94
   444.4 1552.22  449.82 1553.76   457.5 1555.71  476.551555.173   493.4 1554.86
   509.8    1556   565.3 1555.99  791.261559.324  835.221560.358   920.4 1562.52
#Mann= 7 ,-1 , 0
       0     .12       0   189.6     .06       0   401.9     .04       0
  449.82     .04       0  476.55     .06       0  791.26     .12       0
  835.22     .06       0
Bank Sta=401.9,449.82
XS Rating Curve= 0 ,0
Exp/Cntr=0.3,0.1

Type RM Length L Ch R = 1 ,1115.1  ,212,217.8,223.5
XS GIS Cut Line= 4
     2023674.372      147770.776     2023835.817      147924.901
      2024272.54      148376.523      2024259.37      148462.632
#Sta/Elev= 30
       0 1600.26   100.3 1599.05   106.8 1596.76   113.2 1590.39   119.7 1580.54
   129.4 1563.41   132.6 1559.98   142.3 1554.85   187.6 1553.32   242.8 1553.48
   350.8  1554.8   393.4 1553.78     413 1554.87   426.1 1553.51   442.4  1553.6
  453.97 1551.47   475.2 1550.14   501.3 1551.52   517.7 1553.84   534.51554.318
   551.91554.883  575.591555.468   740.2 1557.68   808.9 1559.93  839.271562.035
   854.7 1565.64   880.5 1566.74  893.011568.306   909.5 1569.33   938.6 1575.94
#Mann= 10 ,-1 , 0
       0     .06       0   100.3     .12       0   242.8     .06       0
  453.97     .04       0   501.3     .04       0   534.5     .06       0
   551.9     .08       0  575.59     .12       0  839.27    .016       0
  893.01     .12       0
Bank Sta=453.97,501.3
XS Rating Curve= 0 ,0
Exp/Cntr=0.3,0.1

Type RM Length L Ch R = 1 ,897.3   ,434.3,429.8,425
XS GIS Cut Line= 2
     2023587.566      147883.623     2024022.384      148489.419
#Sta/Elev= 30
       0 1595.19    81.8 1598.03    88.3 1597.22   114.5 1597.06   127.6 1595.76
   130.8 1593.62   134.1 1588.68   143.9 1570.98   147.2 1565.88   150.4 1561.98
     157 1557.32   163.5 1554.23   179.9 1552.03   196.2 1553.05   228.9 1552.44
   281.3 1552.98   327.1 1552.04   356.5 1552.64  398.981550.761   400.5  1550.5
   408.8 1549.37   450.5  1550.7   464.4 1554.71   471.71554.193   588.7 1556.66
   611.6 1558.73  626.481562.514   663.9 1569.79  702.831573.531   745.7 1575.85
#Mann= 9 ,-1 , 0
       0     .06       0   114.5     .12       0   228.9     .06       0
  398.98     .12       0   400.5     .04       0   450.5     .04       0
   471.7     .06       0  626.48     .12       0  702.83     .06       0
Bank Sta=400.5,450.5
XS Rating Curve= 0 ,0
Exp/Cntr=0.3,0.1

Type RM Length L Ch R = 1 ,467.5   ,226,223.9,221.5
XS GIS Cut Line= 2
     2023330.609       148220.04     2023689.984      148617.609
#Sta/Elev= 30
       0 1558.83    29.4 1556.92    71.9 1553.49   111.1 1551.18   124.2 1551.16
   130.7 1550.07   137.2 1547.52   143.8 1546.67   153.6 1546.48   163.4 1547.28
   169.9 1546.55   173.2 1546.52   176.5 1547.04   177.7 1547.49  182.521549.238
   186.3 1550.05  199.861550.949   209.1 1551.24   228.8 1550.83   287.6 1551.27
   307.2 1551.09   352.9 1551.89   431.4 1551.81     451 1552.25     464  1553.5
   470.6 1554.74   490.2 1561.15     500 1563.36   526.1 1567.64   535.9  1568.7
#Mann= 5 ,-1 , 0
       0     .06       0   137.2     .04       0   177.7     .06       0
  182.52     .04       0  199.86     .06       0
Bank Sta=137.2,177.7
XS Rating Curve= 0 ,0
Exp/Cntr=0.3,0.1

Type RM Length L Ch R = 1 ,243.6   ,201,227,263.5
XS GIS Cut Line= 2
     2023140.447      148358.466     2023544.151      148758.234
#Sta/Elev= 30
       0 1561.41    22.9 1561.79    42.4 1561.69    45.7 1561.28    58.8 1555.22
    71.8 1551.48    75.1 1550.93      98 1549.79   124.1 1549.53   169.8 1550.29
   173.1 1550.19  177.721548.516  182.46 1547.02   182.8 1546.34   186.1 1545.65
   195.9 1545.44     209 1545.59   215.5 1546.98  219.29 1548.44     222 1549.27
   228.6 1549.61  247.581548.666   306.9 1550.82   372.2 1549.64   427.7 1552.95
  509.841555.745     529 1556.48   535.5 1557.16   545.3  1559.6   568.2 1567.13
#Mann= 7 ,-1 , 0
       0     .06       0  177.72     .12       0  182.46     .04       0
   215.5     .04       0  219.29     .12       0  247.58     .06       0
  509.84     .12       0
Bank Sta=182.46,215.5
XS Rating Curve= 0 ,0
Exp/Cntr=0.3,0.1

Type RM Length L Ch R = 1 ,16.6    ,0,16.6,35.2
XS GIS Cut Line= 4
     2023103.989      148380.167     2023087.319      148419.245
     2023106.267       148633.69     2023069.462      148734.384
#Sta/Elev= 30
       0 1560.07    16.3 1558.74    68.6 1551.84    84.9  1550.3    94.7 1548.11
   101.2 1547.31   107.7 1547.39   133.8 1549.16   156.6 1549.54   169.7 1548.96
   179.5 1547.61   192.5 1548.01   208.8 1545.79   215.4 1544.85   244.7 1545.35
     248 1545.96   251.2  1547.5   257.8 1549.64     261 1551.49  274.941557.573
   280.5 1559.94     287 1563.65     326 1590.66     339 1596.62   342.2 1598.72
   345.5 1603.48   348.7 1609.45   355.2 1618.36   358.5 1622.18     365 1628.62
#Mann= 4 ,-1 , 0
       0     .06       0   208.8     .04       0     248     .04       0
  274.94     .12       0
Bank Sta=208.8,248
XS Rating Curve= 0 ,0
Exp/Cntr=0.3,0.1

Chan Stop Cuts=-1
Use User Specified Reach Order=0
Composite Channel Slope=5